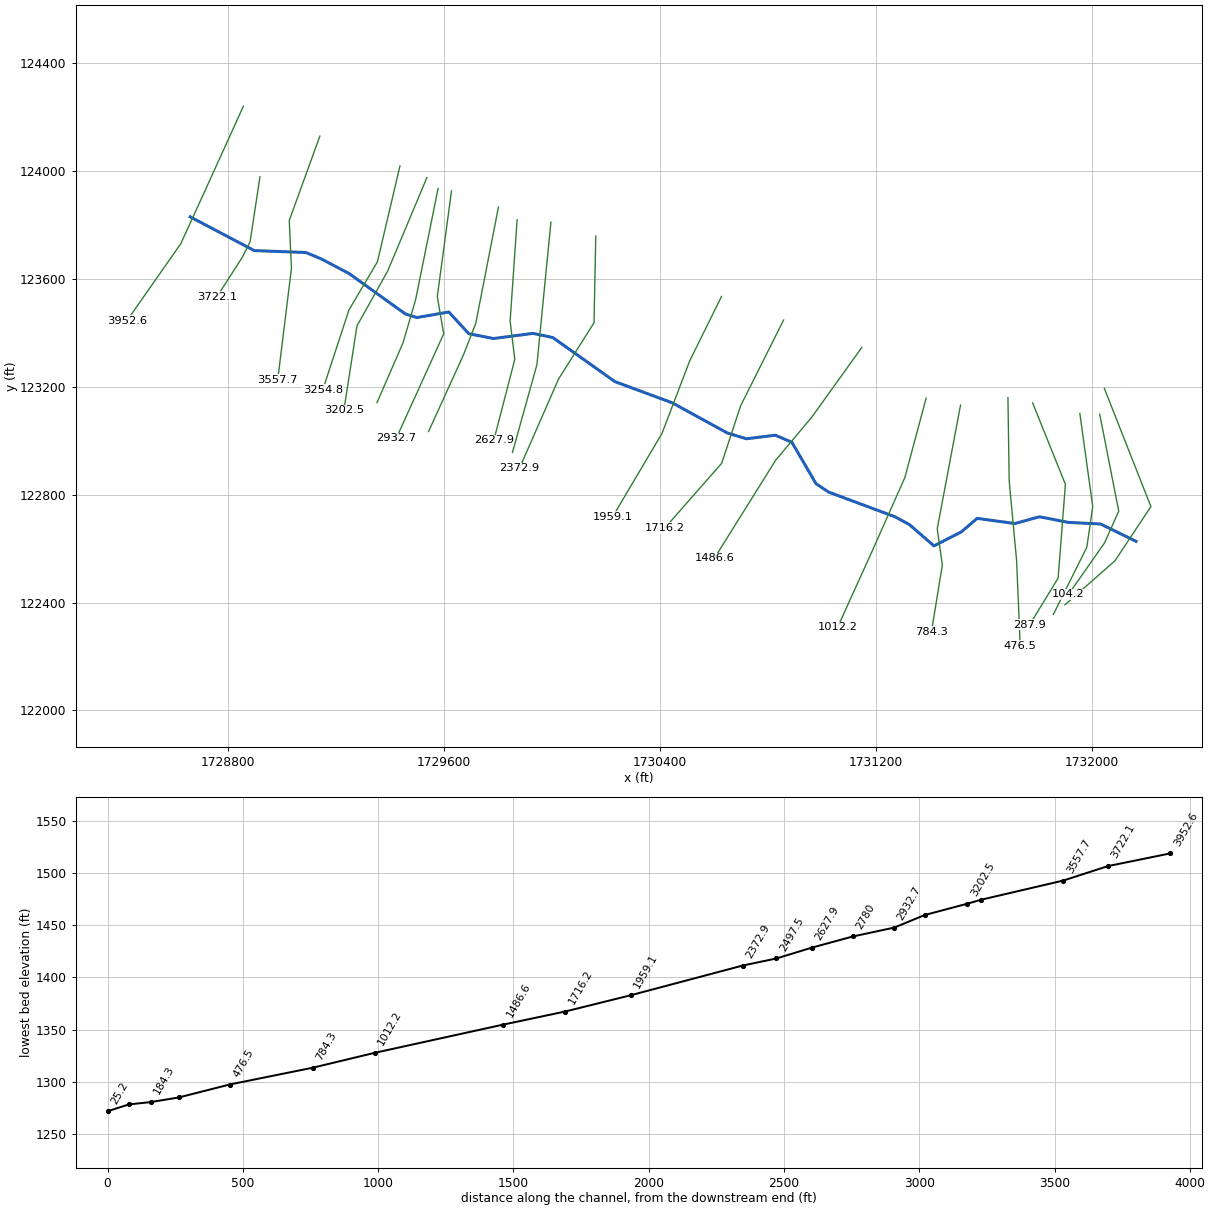
--- Groundhog Branch.prj (project) ---

Proj Title=Groundhog Branch
Current Plan=p01
Default Exp/Contr=0,0
English Units
Geom File=g01
Flow File=f01
Plan File=p01
BEGIN DESCRIPTION:
END DESCRIPTION:
DSS Export Rating Curves= 0
DSS Export Rating Curve Sorted= 0
DSS Export Volume Flow Curves= 0
DXF OffsetX= 0
DXF OffsetY= 0
DXF ScaleX= 0
DXF ScaleY= 0

--- Groundhog Branch.p01 (plan) ---

Plan Title=Floodplain
Program Version=4.00
Geom File=g01
Flow File=f01
K Sum by GR=0
Std Step Tol=0.01
Critical Tol=0.01
Num of Std Step Trials=20
Max Error Tol=0.3
Flow Tol Ratio=0.001
Split Flow NTrial=30
Split Flow Tol=0.02
Split Flow Ratio=0.02
Log Output Level=0
Friction Slope Method=1
Unsteady Friction Slope Method=2
Unsteady Bridges Friction Slope Method=1
Global Log Level=0
CheckData=False
Run HTab=0
Run UNet=0
Run PostProcess=0
UNET Theta=0
UNET Theta Warmup=0
UNET ZTol=0
UNET ZSATol=0
UNET MxIter=0
UNET MaxInSteps=0
UNET DtIC=0
UNET DtMin=0
UNET MaxCRTS=0
UNET WFStab=0
UNET SFStab=0
UNET WFX=0
UNET SFX=0
UNET DSS MLevel=0
UNET DZMax Abort=0
UNET Convert EG Bridges=0
UNET Use Existing IB Tables=0
UNET Froude Limit=0
UNET Froude Power=0
Write IC File=0
Echo Input=False
Echo Output=False
Write Detailed=0

--- Groundhog Branch.f01 (steady flow) ---

Flow Title=NFF Regression Equation
Program Version=4.00
Number of Profiles=1
Profile Names=P100yr
River Rch & RM=Groundhog Branch,Main      ,3952.6
566.2359
River Rch & RM=Groundhog Branch,Main      ,2627.9
617.8532
River Rch & RM=Groundhog Branch,Main      ,287.9
683.5349
Boundary for River Rch & Prof#=Groundhog Branch,Main      ,1
Up Type=0
Dn Type=3
Dn Slope=0.050891

--- Groundhog Branch.g01 (geometry) ---

Geom Title=USGS 10m DEM
Program Version=4.00

River Reach=Groundhog Branch,Main
Reach XY= 30
     1728661.426      123830.529     1728898.452      123705.408
     1729089.838      123698.261     1729145.594      123675.036
     1729249.337      123620.434     1729458.248      123470.197
     1729500.931      123457.011     1729618.644      123477.716
     1729692.526      123397.308     1729783.688      123379.276
     1729929.947      123398.309     1730003.076      123383.283
     1730233.497      123219.578     1730445.861      123140.853
     1730649.524      123029.108     1730720.348      123007.617
     1730827.464      123020.754     1730888.646      122994.594
     1730977.835      122841.143     1731023.782      122810.233
     1731270.224       122718.34     1731322.854      122689.936
     1731414.394      122610.363     1731515.831      122662.368
     1731574.309      122712.492      1731713.82      122693.278
     1731804.878       122718.34     1731912.645      122697.455
     1732031.271      122691.607     1732162.383      122627.347

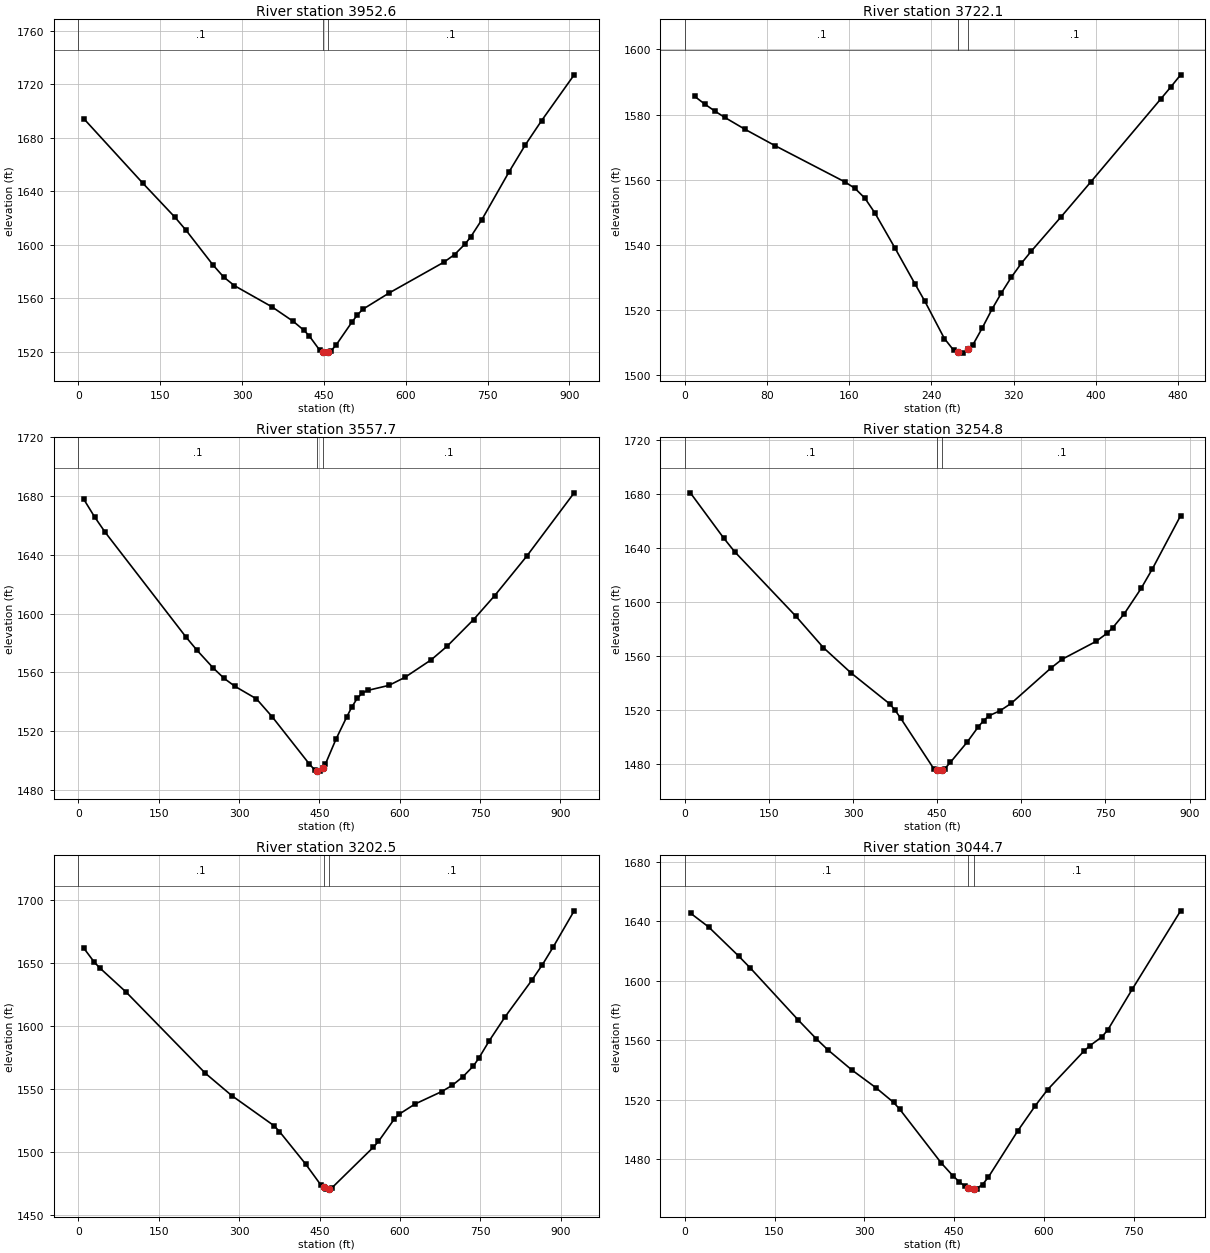
Type RM Length L Ch R = 1 ,3952.6  ,231.1,230.5,229.8
XS GIS Cut Line= 4
     1728858.325      124240.889     1728732.141      123962.394
     1728626.493      123730.815     1728427.024      123445.089
#Sta/Elev= 30
     9.9 1694.27   118.4 1645.86   177.5 1620.28   197.3 1610.79   246.6 1584.87
   266.3 1575.75     286  1569.3   354.7 1553.47   393.9 1542.55   413.4 1535.93
   423.2  1531.7   442.8 1520.77   447.6  1519.8   452.6 1518.79   457.6  1519.5
   462.4 1520.18   472.2 1524.69   501.5 1542.01   511.3 1547.28   521.1 1551.53
   570.2 1563.92   669.8 1586.78   689.7 1592.57   709.6 1600.78   719.6 1606.02
   739.5 1618.57   789.3 1654.32   819.1  1674.5     849 1692.68   908.8 1727.03
#Mann= 3 , 0 , 0
       0      .1       0   447.6    .045       0   457.6      .1       0
Bank Sta=447.6,457.6
XS Rating Curve= 0 ,0
Exp/Cntr=0.3,0.1

Type RM Length L Ch R = 1 ,3722.1  ,154.3,164.5,174.6
XS GIS Cut Line= 4
     1728919.695      123979.018     1728883.182      123738.461
     1728854.399      123680.516     1728760.039      123533.702
#Sta/Elev= 30
     9.7 1585.56    19.5 1583.19    29.2 1581.07    38.9 1579.11    58.4 1575.49
    87.6 1570.46   155.7 1559.29   165.5 1557.32   175.2 1554.29   184.9 1549.77
   204.4 1539.01   223.8 1528.02   233.6 1522.57   252.6 1511.11   261.8 1507.44
     266 1507.07     271 1506.62     276 1507.98   280.3 1509.15   289.5 1514.38
   298.8 1520.04     308 1525.08   317.7 1529.94   327.4  1534.2   337.1 1537.95
   366.2 1548.55   395.3 1559.35   463.1 1584.76   472.8 1588.42   482.5 1592.21
#Mann= 3 , 0 , 0
       0      .1       0     266    .045       0     276      .1       0
Bank Sta=266,276
XS Rating Curve= 0 ,0
Exp/Cntr=0.3,0.1

Type RM Length L Ch R = 1 ,3557.7  ,314.5,302.9,291.2
XS GIS Cut Line= 4
     1729141.338      124129.753     1729028.126      123817.072
     1729036.213      123639.167     1728985.576      123227.186
#Sta/Elev= 30
    10.1 1677.88    30.2 1665.93    50.4 1655.24   201.5 1583.83   221.7 1575.01
   251.9 1562.98   272.1 1555.97   292.2 1550.56   332.5 1542.01   362.2 1529.67
   431.5 1497.54   441.4  1493.6   446.3 1493.21   451.3  1492.8   456.3 1495.18
   461.2 1497.52     481 1514.52   500.7 1529.38   510.6 1536.42   520.5 1542.24
   530.4 1546.01   540.3 1547.75   579.8 1551.16   609.5 1556.57   658.9  1568.6
   688.5 1577.82   737.9 1595.94   777.5 1612.33   836.8 1638.94   925.7 1682.23
#Mann= 3 , 0 , 0
       0      .1       0   446.3    .045       0   456.3      .1       0
Bank Sta=446.3,456.3
XS Rating Curve= 0 ,0
Exp/Cntr=0.3,0.1

Type RM Length L Ch R = 1 ,3254.8  ,51.8,52.3,52.8
XS GIS Cut Line= 4
     1729437.846      124019.236     1729354.285      123663.427
     1729249.159      123485.522      1729152.12      123189.015
#Sta/Elev= 30
     9.9 1681.08    69.1 1647.64    88.9 1637.36   197.6 1589.69     247  1566.2
   296.3 1547.41   365.5 1524.33   375.3 1519.51   385.2 1513.58   444.2 1476.08
   449.1 1475.28   454.1 1474.47   459.1 1475.46   463.9  1476.4   473.7 1481.06
   503.3  1495.9   522.9 1507.13   532.8 1511.97   542.6 1515.62   562.3 1519.33
   582.2 1524.85   652.6  1550.9   672.8 1557.53   733.2 1570.75   753.3 1576.92
   763.3 1581.08   783.5 1591.23   813.7 1610.14   833.8 1624.66   884.1 1664.13
#Mann= 3 , 0 , 0
       0      .1       0   449.1    .045       0   459.1      .1       0
Bank Sta=449.1,459.1
XS Rating Curve= 0 ,0
Exp/Cntr=0.3,0.1

Type RM Length L Ch R = 1 ,3202.5  ,153.2,157.8,162.4
XS GIS Cut Line= 4
      1729537.58      123976.108     1729392.615      123629.949
      1729278.81      123426.221     1729230.291       123113.54
#Sta/Elev= 30
     9.9 1661.87    29.6 1650.69    39.5 1646.22    88.9 1626.97     237 1562.49
   286.4 1544.72   365.4 1520.81   375.3 1516.24   423.9 1490.59   453.1 1473.55
   457.8 1472.12   462.8  1470.6   467.8 1470.99   472.5 1471.36   550.3 1503.77
     560 1508.43   589.2 1525.98   598.9 1530.13   628.4 1538.15   677.9 1547.95
   697.6 1552.89   717.4 1559.66   737.2 1568.29   747.1 1574.38   766.9  1588.4
   796.5  1607.4     846  1636.2   865.7 1648.49   885.5 1662.25   925.1 1691.31
#Mann= 3 , 0 , 0
       0      .1       0   457.8    .045       0   467.8      .1       0
Bank Sta=457.8,467.8
XS Rating Curve= 0 ,0
Exp/Cntr=0.3,0.1

Type RM Length L Ch R = 1 ,3044.7  ,102.9,112,121.2
XS GIS Cut Line= 4
      1729578.93      123935.298     1729496.123      123524.715
     1729449.545      123364.278     1729352.937      123141.735
#Sta/Elev= 30
      10 1645.27    39.9 1636.09    89.8 1616.63   109.7  1608.4   189.5 1573.54
   219.4 1561.01   239.3 1553.36   279.2 1539.88   319.1 1528.04     349 1518.03
     359 1513.56   428.7 1477.23   448.3 1468.56   458.2 1464.85     468 1461.65
   472.8 1460.71   477.8 1459.73   482.8 1459.92   487.6 1460.11   497.5 1462.81
   507.3 1467.83   556.4 1498.94   585.9 1515.97   606.1  1526.6   666.8 1552.54
   676.9 1556.24   697.1 1562.19   707.2 1567.11   747.6  1594.2   828.5 1646.98
#Mann= 3 , 0 , 0
       0      .1       0   472.8    .045       0   482.8      .1       0
Bank Sta=472.8,482.8
XS Rating Curve= 0 ,0
Exp/Cntr=0.3,0.1

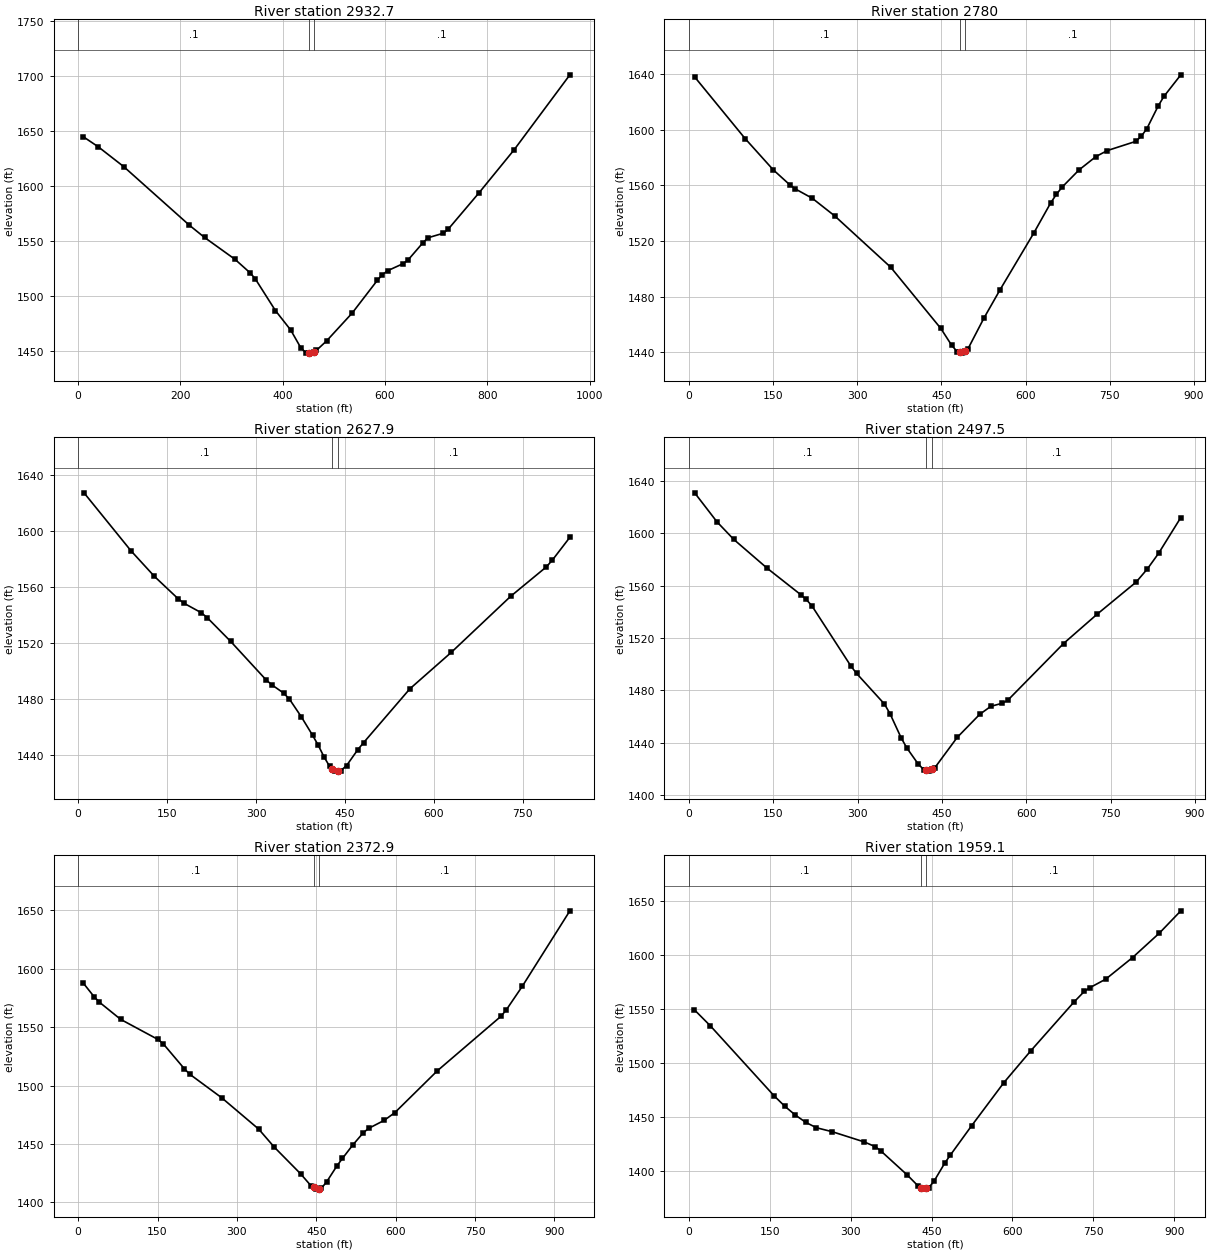
Type RM Length L Ch R = 1 ,2932.7  ,163.7,152.6,141.6
XS GIS Cut Line= 4
     1729628.703      123926.911     1729576.126       123534.85
     1729599.847       123396.84     1729424.071      123009.145
#Sta/Elev= 30
     9.9 1645.02    39.6  1635.7      89 1617.77   217.6 1564.27   247.2 1553.13
   306.6 1533.26   336.2  1520.9   346.1 1515.59   385.7 1486.52   415.6 1468.77
   435.6 1452.37   445.6 1448.05   450.6  1447.9   455.6 1447.74   460.6 1448.95
   465.6 1450.15   485.6 1458.83   535.6 1484.18   585.1  1514.2     595 1519.31
   604.9 1522.83   634.6 1529.14   644.5 1532.39   674.2 1548.42   684.1  1552.9
   713.8    1557   723.7 1560.84   783.1 1593.51   852.4 1633.12   961.3 1701.39
#Mann= 3 , 0 , 0
       0      .1       0   450.6    .045       0   460.6      .1       0
Bank Sta=450.6,460.6
XS Rating Curve= 0 ,0
Exp/Cntr=0.3,0.1

Type RM Length L Ch R = 1 ,2780    ,142.3,152.1,162
XS GIS Cut Line= 4
     1729802.551      123866.939      1729718.45      123435.655
     1729673.165      123319.208      1729543.78      123034.561
#Sta/Elev= 30
      10 1638.01    99.9 1593.69   149.8 1571.31   179.8 1560.33   189.7 1557.39
   219.7 1550.72   259.6 1538.06   359.5 1501.12     449    1457   468.2 1444.97
   477.9 1440.42   482.5 1439.86   487.5 1439.26   492.5 1440.74   497.1 1442.11
   525.9  1464.5   554.7 1484.94   614.8 1525.71     645 1547.45   655.1 1553.56
   665.2 1558.71   695.5 1571.13   725.7 1580.76   745.9 1585.05   796.3 1591.61
   806.4 1595.27   816.5 1600.89   836.7 1617.21   846.8    1624     877 1639.56
#Mann= 3 , 0 , 0
       0      .1       0   482.5    .045       0   492.5      .1       0
Bank Sta=482.5,492.5
XS Rating Curve= 0 ,0
Exp/Cntr=0.3,0.1

Type RM Length L Ch R = 1 ,2627.9  ,139.5,130.4,121.3
XS GIS Cut Line= 4
     1729871.556      123819.498     1729845.679      123444.281
      1729862.93      123301.957     1729785.299      123002.215
#Sta/Elev= 30
     9.9 1627.32    89.1 1585.92   128.7  1567.6   168.3 1551.78   178.2 1548.52
   207.8 1541.63   217.7 1538.13   257.3 1521.13   316.7 1493.81   326.6 1490.18
   346.4 1484.28   356.3 1479.93   376.1 1467.47   395.2 1454.21   404.8 1447.04
   414.3 1438.93   423.9 1431.99   428.5 1430.33   433.5 1428.53   438.5 1428.72
     443  1428.9   452.6  1432.5   471.7 1443.95   481.2 1448.83   559.4 1487.36
   629.3 1513.42   729.2 1553.38   789.2 1574.33   799.1 1579.01   829.1 1595.55
#Mann= 3 , 0 , 0
       0      .1       0   428.5    .045       0   438.5      .1       0
Bank Sta=428.5,438.5
XS Rating Curve= 0 ,0
Exp/Cntr=0.3,0.1

Type RM Length L Ch R = 1 ,2497.5  ,129.3,124.6,120
XS GIS Cut Line= 3
     1729996.628      123810.872     1729944.874      123282.549
     1729854.305       122956.93
#Sta/Elev= 30
     9.9 1630.86    49.7 1608.66    79.4  1595.3     139 1573.22   198.6 1553.06
   208.5 1549.35   218.5 1544.51     288 1498.43   297.9  1492.9   347.6 1469.46
   357.5 1462.07   377.4 1443.55   387.3 1435.99   407.3 1423.83   417.3 1419.42
   422.2 1418.82   427.2  1418.2   432.2 1419.49   437.2 1420.79   477.1 1443.99
     517 1461.57   536.9 1467.72   556.8 1470.03   566.8 1472.26   666.2 1515.69
   725.8 1538.05   795.4 1562.66   815.3 1572.67   835.2 1584.54   874.9    1612
#Mann= 3 , 0 , 0
       0      .1       0   422.2    .045       0   432.2      .1       0
Bank Sta=422.2,432.2
XS Rating Curve= 0 ,0
Exp/Cntr=0.3,0.1

Type RM Length L Ch R = 1 ,2372.9  ,409.8,413.8,417.7
XS GIS Cut Line= 4
     1730162.673      123759.118     1730156.203      123437.811
     1730024.662      123228.639     1729880.324       122898.12
#Sta/Elev= 30
      10 1587.56    30.1  1576.1    40.2 1571.37    80.3 1556.69   150.6 1539.55
   160.7 1535.83   200.9  1514.3   210.9 1509.74   271.2 1489.62   341.1 1462.79
   370.8 1447.26   420.2  1424.6     440 1414.28   444.9 1412.86   449.9 1411.42
   454.9 1411.81   459.7 1412.19   469.6  1417.7   489.4 1431.59   499.3 1437.65
     519 1449.24   538.8 1459.65   548.7 1463.36   578.5 1470.31   598.5 1476.93
   678.7 1512.68   798.9 1559.31   808.9 1564.76     839 1584.84   929.1 1649.55
#Mann= 3 , 0 , 0
       0      .1       0   444.9    .045       0   454.9      .1       0
Bank Sta=444.9,454.9
XS Rating Curve= 0 ,0
Exp/Cntr=0.3,0.1

Type RM Length L Ch R = 1 ,1959.1  ,241.9,242.9,243.8
XS GIS Cut Line= 4
     1730628.013      123535.046     1730510.423      123296.689
     1730407.696      123027.283     1730225.406      122718.953
#Sta/Elev= 30
     9.8  1549.2    39.4 1534.38   157.5 1469.59   177.2 1459.96   196.9  1451.7
   216.6 1444.83   236.3 1439.87   265.8 1436.16   325.4 1426.65   345.3 1422.33
   355.3 1418.61     405 1395.95   424.9 1385.91   429.8 1384.45   434.8 1382.97
   439.8 1383.64   444.7  1384.3   454.7 1390.56   474.6  1407.3   484.5 1414.38
   524.3 1441.81     584  1481.7   633.7 1511.05   713.3 1555.98   733.2 1566.25
   743.2  1569.6     773 1577.61   822.8 1597.66   872.5  1620.3   912.3 1640.94
#Mann= 3 , 0 , 0
       0      .1       0   429.8    .045       0   439.8      .1       0
Bank Sta=429.8,439.8
XS Rating Curve= 0 ,0
Exp/Cntr=0.3,0.1

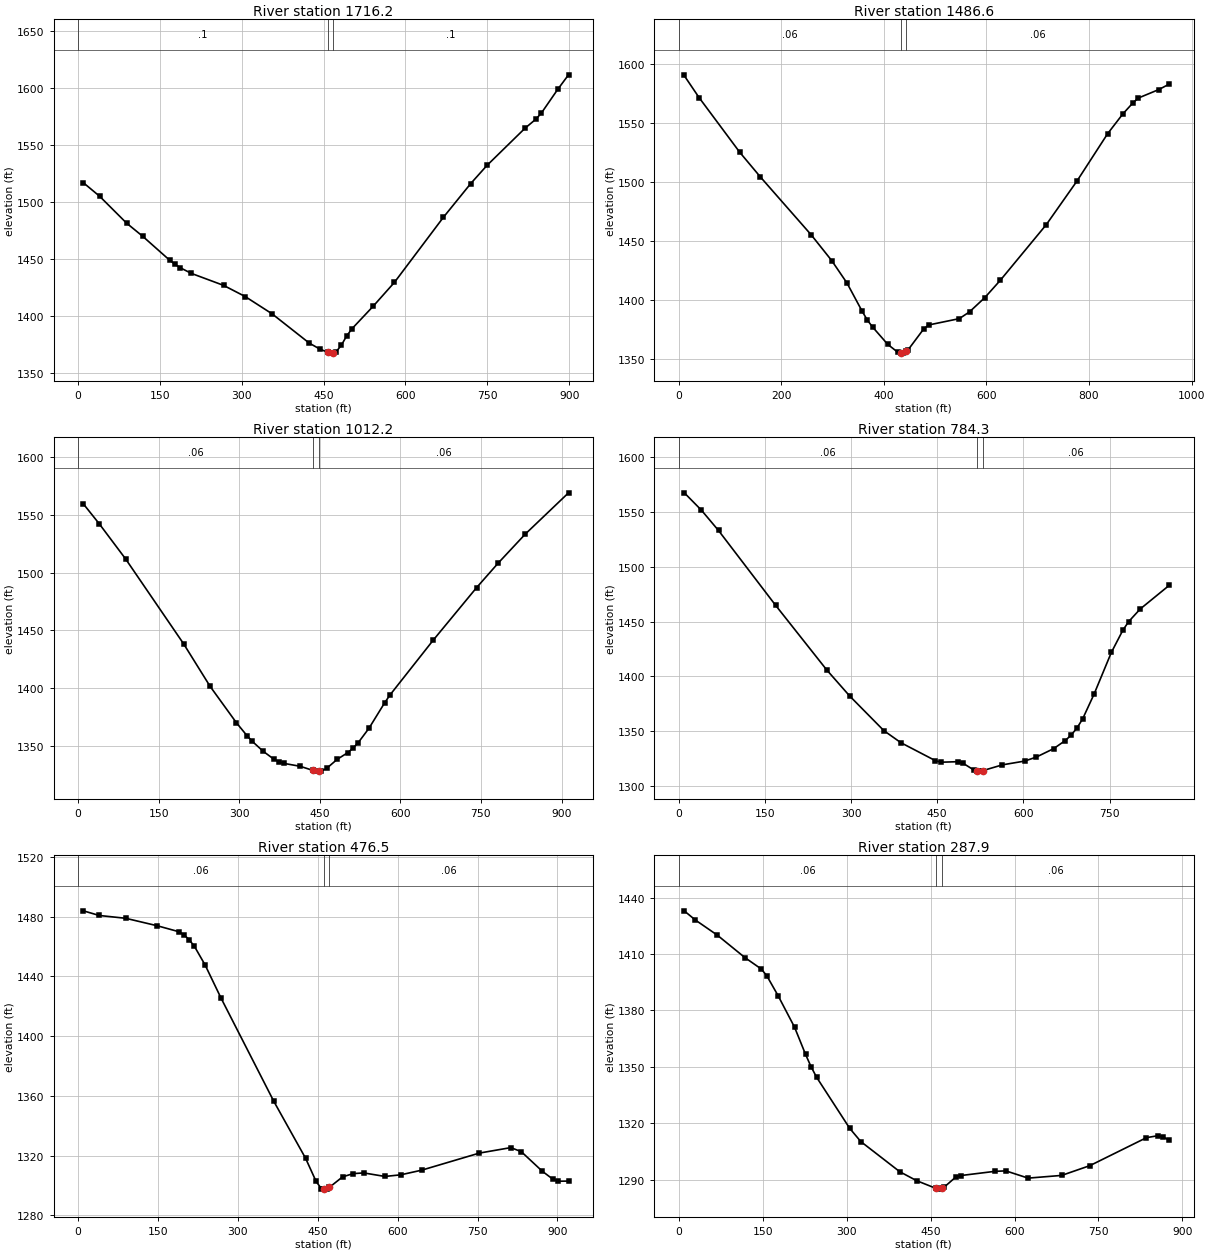
Type RM Length L Ch R = 1 ,1716.2  ,237.6,229.6,221.7
XS GIS Cut Line= 4
     1730857.848      123447.785     1730698.813      123129.713
     1730628.729      122916.767     1730418.478      122676.865
#Sta/Elev= 30
     9.9 1516.74    39.5 1504.96    88.9 1481.39   118.5 1469.82   167.9 1448.84
   177.8 1445.21   187.7 1442.15   207.4 1437.33   266.7 1426.78   306.2 1417.01
   355.6 1401.81   423.8 1376.12   443.3 1370.86   457.8 1368.07   462.8 1367.36
   467.8 1367.87   472.6 1368.37   482.3 1374.17   492.1 1382.31   501.8 1388.67
   540.8 1408.48   579.8 1429.45   669.5  1486.5   719.4 1515.99   749.3 1531.97
     819 1564.59     839 1572.58     849 1577.88   878.9 1598.63   898.8 1611.46
#Mann= 3 , 0 , 0
       0      .1       0   457.8    .045       0   467.8      .1       0
Bank Sta=457.8,467.8
XS Rating Curve= 0 ,0
Exp/Cntr=0.3,0.1

Type RM Length L Ch R = 1 ,1486.6  ,468.9,474.4,480
XS GIS Cut Line= 4
     1731147.582      123346.452     1730962.271      123087.852
     1730828.198      122927.549     1730601.132       122563.69
#Sta/Elev= 30
     9.9 1590.77    39.8  1571.5   119.3    1525   159.1  1504.3   258.5 1455.03
   298.3  1433.3   328.1 1414.26   357.9 1390.13   367.9 1382.76   377.9 1376.97
   407.7 1362.18   427.6 1355.37   432.6 1355.07   437.6 1354.78   442.6 1356.26
   447.5 1357.71   477.4 1375.11   487.3 1378.65   547.1 1384.03     567 1389.77
   596.9  1401.9   626.9 1416.48   716.6 1463.71   776.5 1500.74   836.3 1540.92
   866.2  1557.8   886.2  1567.3   896.2 1571.11   936.1 1578.31     956 1582.84
#Mann= 3 , 0 , 0
       0     .06       0   432.6    .045       0   442.6     .06       0
Bank Sta=432.6,442.6
XS Rating Curve= 0 ,0
Exp/Cntr=0.3,0.1

Type RM Length L Ch R = 1 ,1012.2  ,216.6,227.9,239.8
XS GIS Cut Line= 4
     1731385.502      123158.144     1731306.713      122863.732
     1731186.702      122593.304     1731057.885      122308.762
#Sta/Elev= 30
     9.8  1559.7    39.3 1542.48    88.5 1511.91   196.6 1438.17   245.8 1401.33
   294.9 1369.68   314.6 1358.47   324.5 1353.55   344.2 1345.14   363.9 1338.33
   373.8 1335.93   383.7 1334.45   413.3 1331.99   437.8 1328.33   442.8 1327.78
   447.8 1327.81   452.7 1327.83   462.6  1330.1   482.3 1337.99     502  1343.8
   511.9 1347.72   521.7  1352.6   541.5 1364.95     571 1387.28   580.9 1394.01
   661.1 1441.41   741.7 1486.93     782 1508.27   832.4 1533.42     913 1569.27
#Mann= 3 , 0 , 0
       0     .06       0   437.8    .045       0   447.8     .06       0
Bank Sta=437.8,447.8
XS Rating Curve= 0 ,0
Exp/Cntr=0.3,0.1

Type RM Length L Ch R = 1 ,784.3   ,308.2,307.8,306.8
XS GIS Cut Line= 4
     1731512.861      123132.409     1731426.604      122674.169
     1731445.473      122539.393      1731405.04      122291.405
#Sta/Elev= 30
     9.9 1567.37    39.7 1551.52    69.4 1533.02   168.7 1464.85   257.9 1405.79
   297.6 1382.15   357.2 1350.51   386.9 1339.51   446.4 1323.27   456.4 1321.73
   485.7  1322.2   495.4 1320.66   514.9 1314.26   519.6 1313.94   524.6  1313.6
   529.6 1314.09   563.5 1319.33   602.4 1322.78   622.5 1326.42   652.6 1334.07
   672.7 1341.41   682.8 1346.28   692.8 1352.57   702.9 1360.96     723 1383.77
   753.1 1421.84   773.2 1442.14   783.3 1449.99   803.4 1461.47   853.6 1482.91
#Mann= 3 , 0 , 0
       0     .06       0   519.6    .045       0   529.6     .06       0
Bank Sta=519.6,529.6
XS Rating Curve= 0 ,0
Exp/Cntr=0.3,0.1

Type RM Length L Ch R = 1 ,476.5   ,192.1,188.5,185
XS GIS Cut Line= 4
     1731688.328      123159.984     1731692.875      122852.065
     1731720.416      122555.566     1731733.605      122240.901
#Sta/Elev= 30
     9.9 1483.97    39.7 1480.86    89.4 1478.97     149 1473.93   188.7 1470.03
   198.7 1467.96   208.6  1464.6   218.5 1460.11   238.4 1447.74   268.2 1425.62
   367.5 1356.27   427.1 1318.15   446.9 1302.59   456.8 1297.78   461.8 1297.63
   466.8 1297.47   471.8 1298.66   496.5 1305.68   516.4 1307.86   536.2 1308.34
     576 1305.97   605.7 1307.05   645.1 1310.18   753.4 1321.63   812.4 1325.29
   832.1 1322.55   871.5 1309.45   891.1 1304.18     901 1302.76   920.7 1302.87
#Mann= 3 , 0 , 0
       0     .06       0   461.8    .045       0   471.8     .06       0
Bank Sta=461.8,471.8
XS Rating Curve= 0 ,0
Exp/Cntr=0.3,0.1

Type RM Length L Ch R = 1 ,287.9   ,105,103.7,102.3
XS GIS Cut Line= 4
     1731779.718      123140.495     1731901.016      122838.596
     1731874.061      122490.874     1731768.936       122318.36
#Sta/Elev= 30
     9.9 1432.97    29.6 1428.15      69 1420.06   118.3 1408.14   147.9 1401.99
   157.7 1398.34   177.5 1387.95     207 1371.16   226.8 1356.61   236.6 1350.08
   246.5 1344.48   305.6 1317.35   325.4 1310.33   395.1 1294.28     425 1289.55
   459.9 1285.41   464.9 1285.04   469.9 1285.64   474.8 1286.22   494.8  1291.4
   504.7 1292.28   564.5 1294.48   584.4 1294.75   624.3 1290.89   684.2 1292.33
   734.7 1297.54   835.7  1312.4   855.9 1313.42     866 1312.75   876.1 1311.04
#Mann= 3 , 0 , 0
       0     .06       0   459.9    .045       0   469.9     .06       0
Bank Sta=459.9,469.9
XS Rating Curve= 0 ,0
Exp/Cntr=0.3,0.1

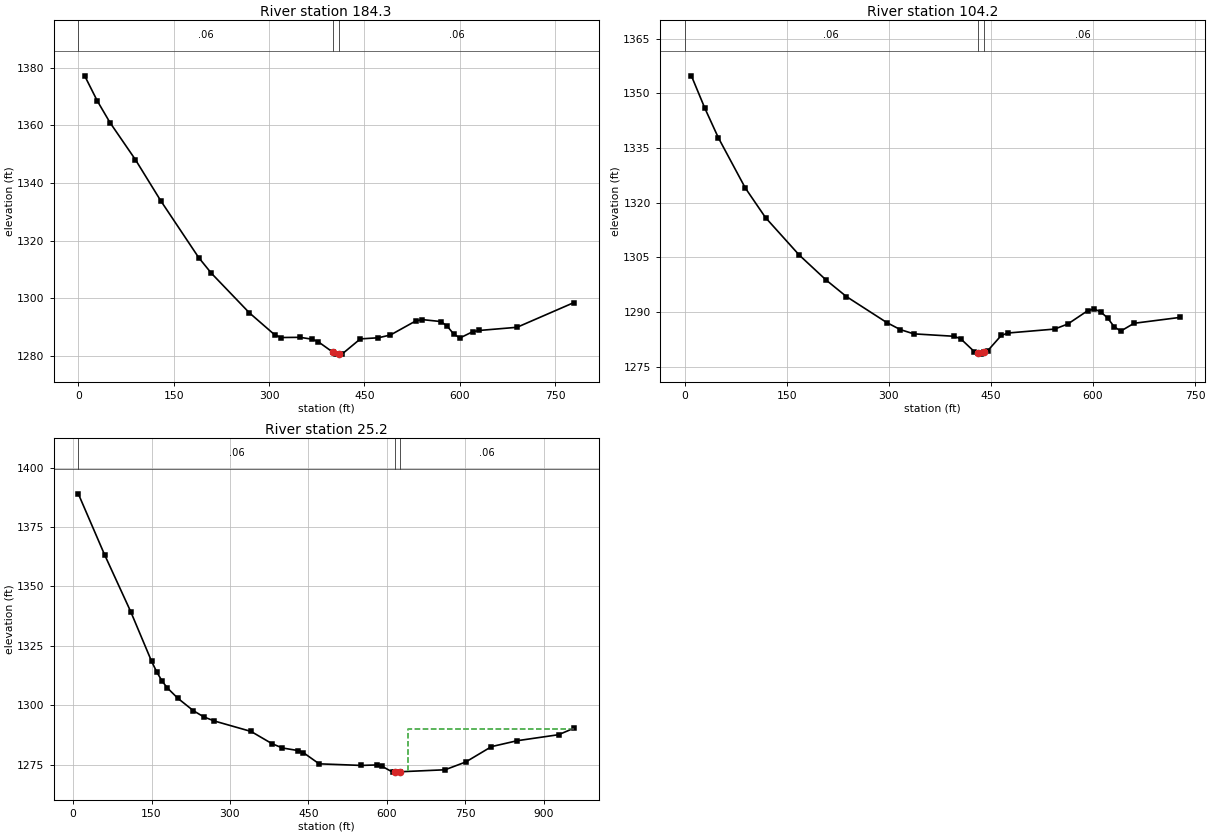
Type RM Length L Ch R = 1 ,184.3   ,85.6,80,74.5
XS GIS Cut Line= 4
     1731954.452      123101.463     1732002.141      122756.079
     1731980.464      122605.787     1731856.184      122355.781
#Sta/Elev= 30
      10 1377.18    29.9 1368.45    49.8 1360.96    89.7 1348.13   129.5 1333.89
   189.3 1314.13   209.2 1308.71     269 1294.96   308.8 1287.34   318.8 1286.39
   348.7 1286.46   367.6 1285.81   377.1 1284.96   400.6 1281.27   405.6 1280.63
   410.6 1280.67   415.1 1280.71   443.6 1285.91     472 1286.31     491 1287.27
   530.4 1292.11   540.4 1292.62   570.3 1291.93   580.3 1290.32   590.2 1287.64
   600.2 1286.24   620.2 1288.39   630.1 1288.83     690 1289.94   779.7 1298.53
#Mann= 3 , 0 , 0
       0     .06       0   400.6    .045       0   410.6     .06       0
Bank Sta=400.6,410.6
XS Rating Curve= 0 ,0
Exp/Cntr=0.3,0.1

Type RM Length L Ch R = 1 ,104.2   ,82.3,79,75.7
XS GIS Cut Line= 4
     1732027.972      123098.753     1732098.422       122739.28
     1732046.036      122621.864     1731912.363      122430.385
#Sta/Elev= 30
     9.9 1354.84    29.7 1345.92    49.5 1337.83    89.1 1324.03   118.8  1315.9
   168.3 1305.62   207.9 1298.74   237.6 1294.22     297 1287.07   316.8 1285.14
   336.6 1283.97     396  1283.3   405.9 1282.57   425.7 1279.06   430.5 1278.74
   435.5  1278.4   440.5 1278.88   445.4 1279.35   465.2 1283.53   475.1  1284.2
   543.5 1285.28     563 1286.67   592.2 1290.33   601.9  1290.8   611.6 1289.95
   621.4 1288.34   631.1 1285.92   640.8 1284.73   660.3 1286.87   728.4  1288.5
#Mann= 3 , 0 , 0
       0     .06       0   430.5    .045       0   440.5     .06       0
Bank Sta=430.5,440.5
XS Rating Curve= 0 ,0
Exp/Cntr=0.3,0.1

Type RM Length L Ch R = 1 ,25.2    ,23.3,25.2,27.2
XS GIS Cut Line= 4
     1732045.304      123194.037     1732217.464      122756.079
     1732084.513      122555.207     1731899.537      122391.909
#Sta/Elev= 30
      10 1388.94    60.1 1363.39   110.1 1339.44   150.2 1318.45   160.2 1313.93
   170.2 1310.18   180.2 1307.32   200.2 1302.97   230.3 1297.68   250.3 1295.08
   270.3 1293.38   340.4 1288.99   380.5 1283.84   400.5 1282.03   430.5 1280.95
   440.5 1280.07   470.6 1275.37   550.9  1274.7     581  1274.9     591 1274.32
   611.1  1271.9   616.1 1271.89   621.1 1271.88   626.1 1272.04   711.5 1272.87
   750.9 1276.13   800.3 1282.61   849.6  1285.1   928.6 1287.62   958.2 1290.37
#Mann= 3 , 0 , 0
      10     .06       0   616.1    .045       0   626.1     .06       0
#XS Ineff= 2 , 0
                          640.04         1289.96
Permanent Ineff=
       F       F
Bank Sta=616.1,626.1
XS Rating Curve= 0 ,0
Exp/Cntr=0.3,0.1

Chan Stop Cuts=-1
Use User Specified Reach Order=0